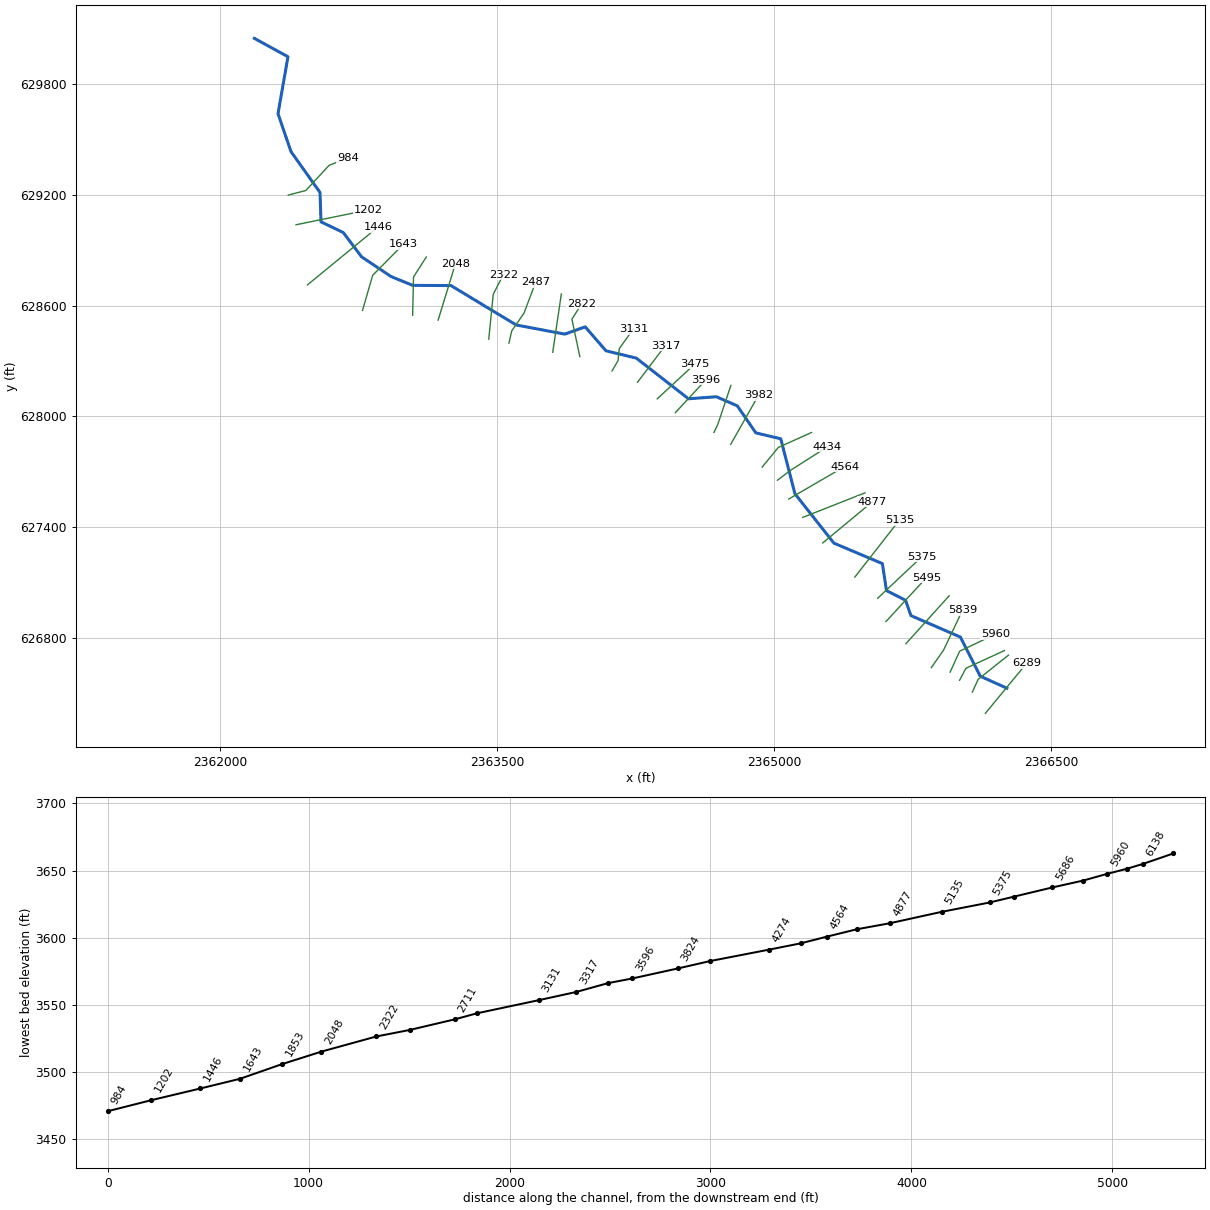
--- NARROWRDG.prj (project) ---

Proj Title=NARROWRDG
Current Plan=p01
Default Exp/Contr=0,0
English Units
Geom File=g01
Flow File=f01
Plan File=p01
BEGIN DESCRIPTION:
----------MODEL BY WOOD PLC 2022----------
AFH study
Randolph County, WV
HEC-RAS Version: RAS 6.2
Vertical Datum: NAVD88
Projection: NAD 1983 StatePlane West Virginia S FIPS 4702 (US Feet)
Terrain: 1-meter LIDAR (FEMA Region III 3DEP collected 2016-2018)
Land Use: 2019 NLCD
Hydrologic Method:
WV SIR2010-5033 regression equations
Additional Model Notes:
None
END DESCRIPTION:
DSS Export Rating Curves= 0
DSS Export Rating Curve Sorted= 0
DSS Export Volume Flow Curves= 0
DXF OffsetX= 0
DXF OffsetY= 0
DXF ScaleX= 0
DXF ScaleY= 0

--- NARROWRDG.p01 (plan) ---

Plan Title=Floodplain
Program Version=6.20
Short Identifier=Floodplain
Geom File=g01
Flow File=f01
Subcritical Flow
K Sum by GR= 0
Std Step Tol= 0.01
Critical Tol= 0.01
Num of Std Step Trials= 20
Max Error Tol= 0.3
Flow Tol Ratio= 0.001
Split Flow NTrial= 30
Split Flow Tol= 0.02
Split Flow Ratio= 0.02
Log Output Level= 0
Friction Slope Method= 1
Unsteady Friction Slope Method= 2
Unsteady Bridges Friction Slope Method= 1
Parabolic Critical Depth
Global Vel Dist= 0 , 0 , 0
Global Log Level= 0
CheckData=True
Encroach Param=-1 ,0,0, 0
Mapping Interval=1HOUR
Computation Time Step Use Courant=        0
Computation Time Step Use Time Series=    0
Computation Time Step Count To Double=0
Computation Time Step Max Doubling=0
Computation Time Step Max Halving=0
Computation Time Step Residence Courant=0
Run HTab= 0
Run UNet= 0
Run Sediment= 0
Run PostProcess= 0
Run WQNet= 0
Run RASMapper=-1
UNET Theta= 0
UNET Theta Warmup= 0
UNET ZTol= 0
UNET ZSATol= 0
UNET MxIter= 0
UNET Max Iter WO Improvement= 0
UNET MaxInSteps= 0
UNET DtIC= 0
UNET DtMin= 0
UNET MaxCRTS= 0
UNET WFStab= 0
UNET SFStab= 0
UNET WFX= 1
UNET SFX= 1
UNET Gravity=32.174
UNET 1D Methodology=Finite Difference
UNET DSS MLevel= 1
UNET Pardiso=0
UNET DZMax Abort= 0
UNET Use Existing IB Tables= 0
UNET Froude Reduction=False
UNET Froude Limit= 0
UNET Froude Power= 0
UNET D1 Cores= 0
UNET WindReference=Eulerian
UNET WindDragFormulation=Hsu (1988)
UNET D2 Coriolis=0
UNET D2 Cores= 0
UNET D2 Theta= 1
UNET D2 Theta Warmup= 1
UNET D2 Z Tol= 0.01
UNET D2 Volume Tol= 0.01
UNET D2 Max Iterations= 20
UNET D2 Equation= 0
UNET D2 RampUpFraction=0.1
UNET D2 TimeSlices= 1
UNET D2 Turbulence Formulation=Non-Conservative (original)
UNET D2 Eddy Viscosity=0.3
UNET D2 Transverse Eddy Viscosity=0.1
UNET D2 Smagorinsky Mixing=0
UNET D2 BCVolumeCheck=0
UNET D2 Cores=0
UNET D2 SolverType=PARDISO (Direct)
UNET D2 Minimum Iterations= 2147483647
UNET D2 Maximum Iterations= 2147483647
UNET D2 Restart Number= 10
UNET D2 Relaxation Coeff=1.3
UNET D2 SOR Precondition Iterations= 10
UNET D2 ILUT Maximum Fill= 8
UNET D2 ILUT Tolerance=1E-08
UNET D1D2 MaxIter= 0
UNET D1D2 ZTol=0.01
UNET D1D2 QTol=0.1
UNET D1D2 MinQTol=1
Write IC File= 0
Write IC File at Fixed DateTime=0
Write IC File at Sim End=0
Echo Input=False
Echo Parameters=False
Echo Output=False
Write Detailed= 0
HDF Write Warmup=0
HDF Write Time Slices=0
HDF Flush=0
HDF Compression= 1
HDF Chunk Size= 1
HDF Spatial Parts= 1
HDF Use Max Rows=0
HDF Fixed Rows= 1
Calibration Method= 0
Calibration Iterations= 20
Calibration Max Change=0.05
Calibration Tolerance=0.2
Calibration Maximum=1.5
Calibration Minimum=0.5
Calibration Optimization Method= 1
WQ AD Non Conservative
WQ ULTIMATE=-1
WQ Max Comp Step=1HOUR
WQ Output Interval=15MIN
WQ Output Selected Increments= 0
WQ Output face flow=0
WQ Output face velocity=0
WQ Output face area=0
WQ Output face dispersion=0
WQ Output cell volume=0
WQ Output cell surface area=0
WQ Output cell continuity=0
WQ Output cumulative cell continuity=0
WQ Output face conc=0
WQ Output face dconc_dx=0
WQ Output face courant=0
WQ Output face peclet=0
WQ Output face adv mass=0
WQ Output face disp mass=0
WQ Output cell mass=0
WQ Output cell source sink temp=0
WQ Output nsm pathways=0
WQ Output nsm derived pathways=0
WQ Create Restart=0
WQ Fixed Restart=0
WQ System Summary=0
WQ Write To DSS=0
Sorting and Armoring Iterations= 10
XS Update Threshold= 0.02
Bed Roughness Predictor= 0
Hydraulics Update Threshold= 0.02
Energy Slope Method= 1
Volume Change Method= 1
Sediment Retention Method= 0
Sediment TS Multiplier= 1
Warm Up Method= 0
XS Weighting Method= 0
Number of US Weighted Cross Sections= 1
Number of DS Weighted Cross Sections= 1
Upstream XS Weight=0
Main XS Weight=1
Downstream XS Weight=0
Number of DS XS's Weighted with US Boundary= 1
Upstream Boundary Weight= 1
Weight of XSs Associated with US Boundary= 0
Number of US XS's Weighted with DS Boundary= 1
Downstream Boundary Weight= 0.5
Weight of XSs Associated with DS Boundary= 0.5
Percentile Method= 0
Sediment Output Level= 3
Mass or Volume Output= 0
Output Increment Type= 1
Profile and TS Output Increment= 1
Transport Output Increment 1
XS Output Flag= 0
XS Output Increment= 10
Read HDF5 Sediment Hotstart= 0
Sediment Hotstart Type= 0
Write Gradation File= 0
Read Gradation Hotstart= 0
Write HDF5 File= 1
Write Binary Output= 1
Write DSS Sediment File= 0
DSS Sediment Output Type= 1
SV Curve= 0
Specific Gage Flag= 0
Subcell Erosion Methods= 0
Subcell Deposition Methods= 0
Advection Scheme= 1
Matrix Solver= 0
Implicit Weighting Factor= 1
Maximum Outer Loop Convergence Iterations= 5
Convergence Maximum Absolute= 0.001
Convergence RMSE= 0.0001
Grain Fractions Max Abs Error= 0.001
Max Subgrid Regions= 1
Max Subgrid Length Scale= 3.402823E+38
Initial Layer Thickness= 3.402823E+38
Min Layer Thickness= 3.402823E+38
Max Layer Thickness= 3.402823E+38
Number of Layers= 5

--- NARROWRDG.f01 (steady flow) ---

Flow Title=Flow
Program Version=6.20
Number of Profiles= 1
Profile Names=P100yr
River Rch & RM=NARROWRDG,Main,6289
     375
Boundary for River Rch & Prof#=NARROWRDG,Main            , 1
Up Type= 0
Dn Type= 3
Dn Slope=0.08375
DSS Import GetInterval= 0
DSS Import GetPeak= 0
DSS Import FillOption= 0

--- NARROWRDG.g01 (geometry) ---

Geom Title=Geometry
Program Version=6.20

River Reach=NARROWRDG       ,Main
Reach XY= 30
2366259.87480055626528.106839741     2366115.903      626592.949
      2366008.09      626804.928     2365740.084      626921.312
     2365711.213      627004.1892365607.63158972 627056.94728179
     2365585.694      627202.844     2365323.094      627313.652
     2365111.922      627581.115     2365035.069      627879.086
     2364900.015      627911.054     2364799.609      628057.471
     2364686.545      628106.733     2364535.286      628095.665
     2364252.517      628316.043 2364088.2980257628355.622743465
     2363975.801      628485.4252363865.14307709628446.018999557
2363602.37652111628495.3566220422363248.50830695628708.915561319
     2363041.146       628710.14     2362924.392      628757.883
     2362764.843      628864.394     2362665.362      628996.184
2362544.74657566629054.070200408     2362539.322      629213.352
     2362382.205      629434.533     2362311.796      629640.061
     2362365.772      629948.444     2362183.519      630048.175

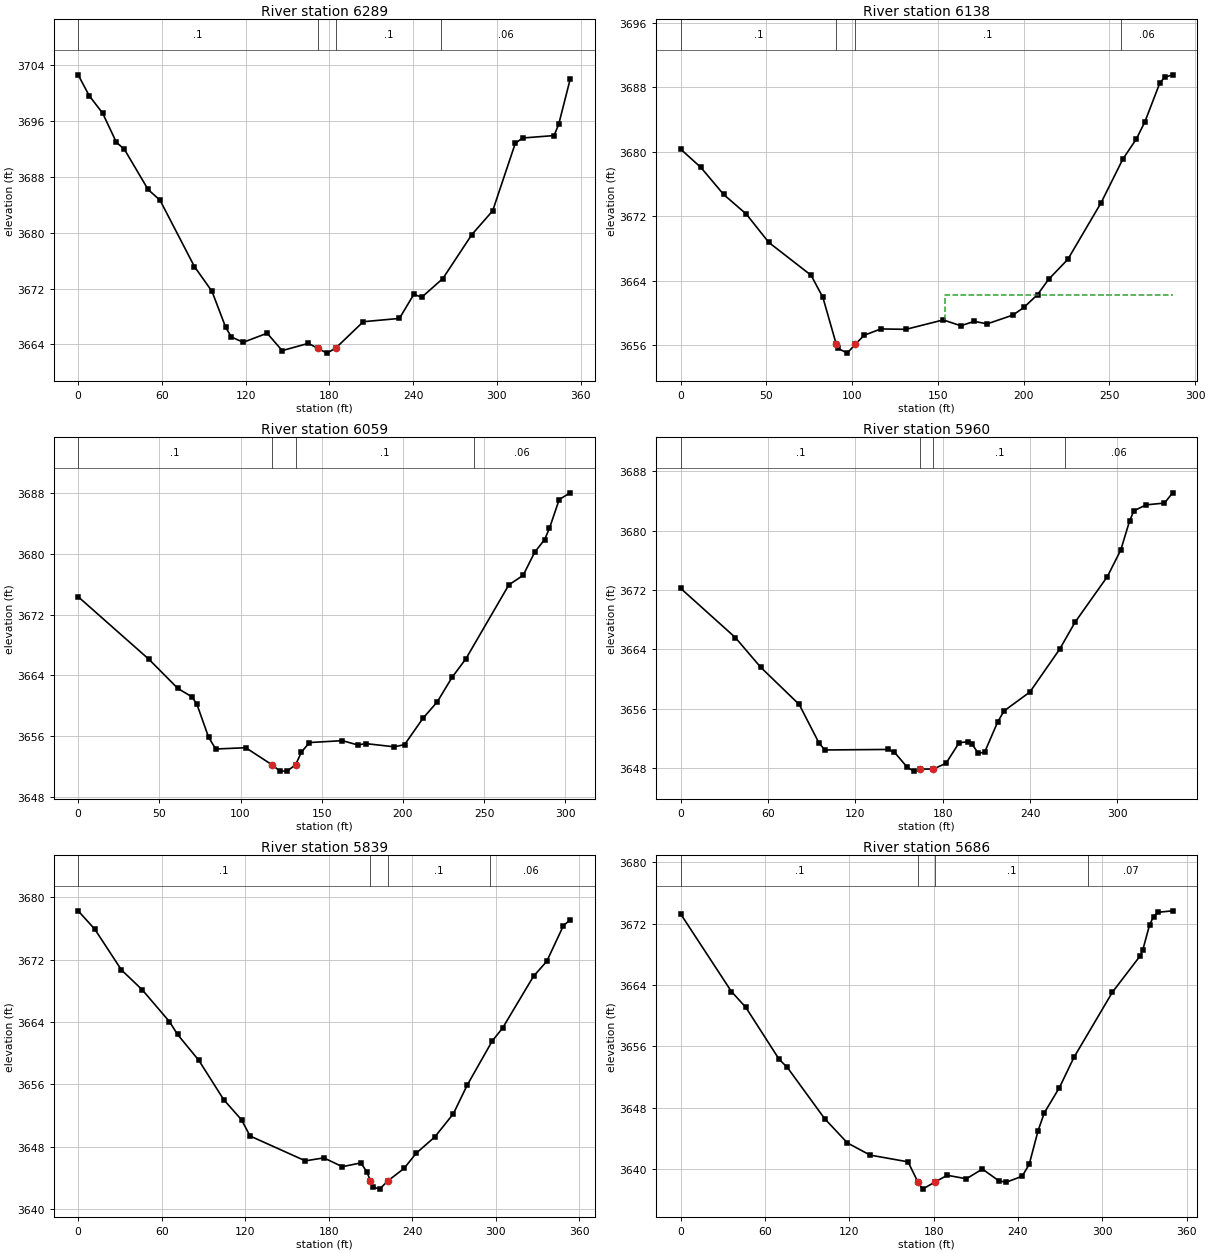
Type RM Length L Ch R = 1 ,6289    ,151.5,150.4,150
XS GIS Cut Line= 2
2366143.13730646626391.6404096212366367.60188092626663.606403293
#Sta/Elev= 30
       0 3702.62     7.9 3699.64    17.6 3697.11    27.4 3692.95    33.1 3691.96
    50.1  3686.2    58.7 3684.65    83.3 3675.16    95.9 3671.61   105.7 3666.46
   109.8 3665.07   118.3 3664.31   135.4 3665.61   146.2 3663.12     165 3664.16
   171.53663.464   178.3 3662.76   184.63663.487   204.3 3667.26   230.2 3667.73
   240.5 3671.18   246.2 3670.77   261.3 3673.44   282.1 3679.74     297 3683.14
   313.2  3692.8   318.4 3693.57     341 3693.92   344.3 3695.52   352.6 3702.04
#Mann= 4, -1 ,  0
       0     0.1       0   171.5   0.045       0   184.6     0.1       0
     260    0.06       0
Bank Sta=171.5,184.6
XS Rating Curve= 0 ,0
Exp/Cntr(USF)=0,0
Exp/Cntr=0.3,0.1

Type RM Length L Ch R = 1 ,6138    ,80.6,79.2,78.2
XS GIS Cut Line= 3
2366072.56340615626506.3383560592366104.47885928626576.207321024
2366268.62414307626707.271465971
#Sta/Elev= 30
       0 3680.32    11.9 3678.03    25.1 3674.69    38.3 3672.26    51.5 3668.73
    76.1 3664.67      83 3661.92    90.83656.107    91.8  3655.6    97.2 3655.01
   101.93656.107   107.1 3657.23   116.8 3658.01   131.4 3657.96   153.2 3659.13
   163.4  3658.4   171.2 3658.95   178.8 3658.64   193.8 3659.73   200.2 3660.68
   208.2 3662.28   214.6 3664.16   225.8 3666.64   245.2 3673.66   257.9 3679.08
   265.8 3681.58   270.7 3683.68   279.4 3688.49   282.2 3689.22   286.9 3689.52
#Mann= 4, -1 ,  0
       0     0.1       0    90.8   0.045       0   101.9     0.1       0
  256.81    0.06       0
#XS Ineff= 2 , 0
                          153.99         3662.26
Permanent Ineff=
       F       F
Bank Sta=90.8,101.9
XS Rating Curve= 0 ,0
Exp/Cntr(USF)=0,0
Exp/Cntr=0.3,0.1

Type RM Length L Ch R = 1 ,6059    ,98.8,98.9,99
XS GIS Cut Line= 3
2366003.72487426626570.9084858982366038.05335677626635.913484695
2366246.50758887 626731.81411775
#Sta/Elev= 30
       0 3674.36    43.5 3666.14    61.4 3662.29    70.1 3661.18    73.1 3660.22
    80.3 3655.88    84.7 3654.32   103.2 3654.49   119.23652.264   124.3 3651.41
   128.7 3651.42   133.9 3652.25   137.5 3653.92   142.4 3655.17   162.7 3655.42
   172.2 3654.85   177.1 3655.03   194.7 3654.61     201  3654.9   212.3 3658.36
   221.1 3660.52   230.2 3663.74   238.8 3666.21   265.2 3675.92     274 3677.17
   281.1 3680.22   287.2 3681.87   290.2 3683.37   296.2 3687.15     303 3688.03
#Mann= 4, -1 ,  0
       0     0.1       0   119.2   0.045       0   133.9     0.1       0
  243.51    0.06       0
Bank Sta=119.2,133.9
XS Rating Curve= 0 ,0
Exp/Cntr(USF)=0,0
Exp/Cntr=0.3,0.1

Type RM Length L Ch R = 1 ,5960    ,117.2,121.2,124.4
XS GIS Cut Line= 3
 2365952.5658656626614.9507869472366003.83980164626728.140889779
 2366196.6636183626820.170438638
#Sta/Elev= 30
       0 3672.24    37.6  3665.6    55.1 3661.58    81.5 3656.58    95.1 3651.38
    99.1 3650.45   142.4 3650.52   146.8 3650.16   155.7 3648.12   160.1  3647.6
   164.5 3647.88   173.6 3647.88   182.3 3648.66   191.3 3651.42   197.3 3651.56
     200 3651.29   204.4 3650.02   208.8 3650.14   217.7 3654.19   222.1  3655.7
   239.9 3658.26   260.3 3664.02   270.9 3667.66   293.1 3673.81   302.3 3677.39
   308.3 3681.28   311.3 3682.67   319.7 3683.47   332.3 3683.71   337.9 3685.09
#Mann= 4, -1 ,  0
       0     0.1       0   164.5   0.045       0   173.6     0.1       0
  264.26    0.06       0
Bank Sta=164.5,173.6
XS Rating Curve= 0 ,0
Exp/Cntr(USF)=0,0
Exp/Cntr=0.3,0.1

Type RM Length L Ch R = 1 ,5839    ,153.9,152.7,150.3
XS GIS Cut Line= 3
2365850.63349173626639.3682521712365917.05213743626734.683321659
2366018.83655553626949.034405531
#Sta/Elev= 30
       0 3678.27      12  3675.9    31.1 3670.68    46.1 3668.12    65.6 3664.04
    71.4  3662.4    86.7 3659.07   104.6 3654.02   117.4 3651.43   123.5 3649.36
   163.2 3646.17   176.5 3646.55   189.8 3645.42   203.1 3645.91   207.5 3644.72
   209.93643.614   211.9 3642.82   216.5 3642.54   222.63643.612   234.1  3645.2
   242.9 3647.16   256.2 3649.24   269.5 3652.21   279.5  3655.9   297.5 3661.57
   304.9 3663.22   327.1 3669.87   336.6 3671.78   348.6 3676.37   353.5 3677.12
#Mann= 4, -1 ,  0
       0     0.1       0   209.9   0.045       0   222.6     0.1       0
  296.17    0.06       0
Bank Sta=209.9,222.6
XS Rating Curve= 0 ,0
Exp/Cntr(USF)=0,0
Exp/Cntr=0.3,0.1

Type RM Length L Ch R = 1 ,5686    ,189.9,191.4,189.5
XS GIS Cut Line= 2
 2365713.1175128626769.0563962942365947.55616451627028.938135915
#Sta/Elev= 30
       0 3673.27    36.2 3663.15    46.4  3661.1    70.2 3654.31    75.9 3653.29
   102.5 3646.61   118.7 3643.45   134.8 3641.87   161.8 3640.99   168.93638.338
   172.2 3637.44   180.7 3638.34   189.7 3639.24   203.3 3638.79   214.7 3640.05
   226.4 3638.52   231.5 3638.33     243 3639.12     248 3640.67   254.3 3645.04
   258.7 3647.35   269.5 3650.66   279.8 3654.58   307.2 3663.07     327 3667.81
   328.8 3668.58   333.6 3671.82   336.4  3672.9   339.6 3673.46     350 3673.65
#Mann= 4, -1 ,  0
       0     0.1       0   168.9   0.045       0   180.7     0.1       0
     290    0.07       0
Bank Sta=168.9,180.7
XS Rating Curve= 0 ,0
Exp/Cntr(USF)=0,0
Exp/Cntr=0.3,0.1

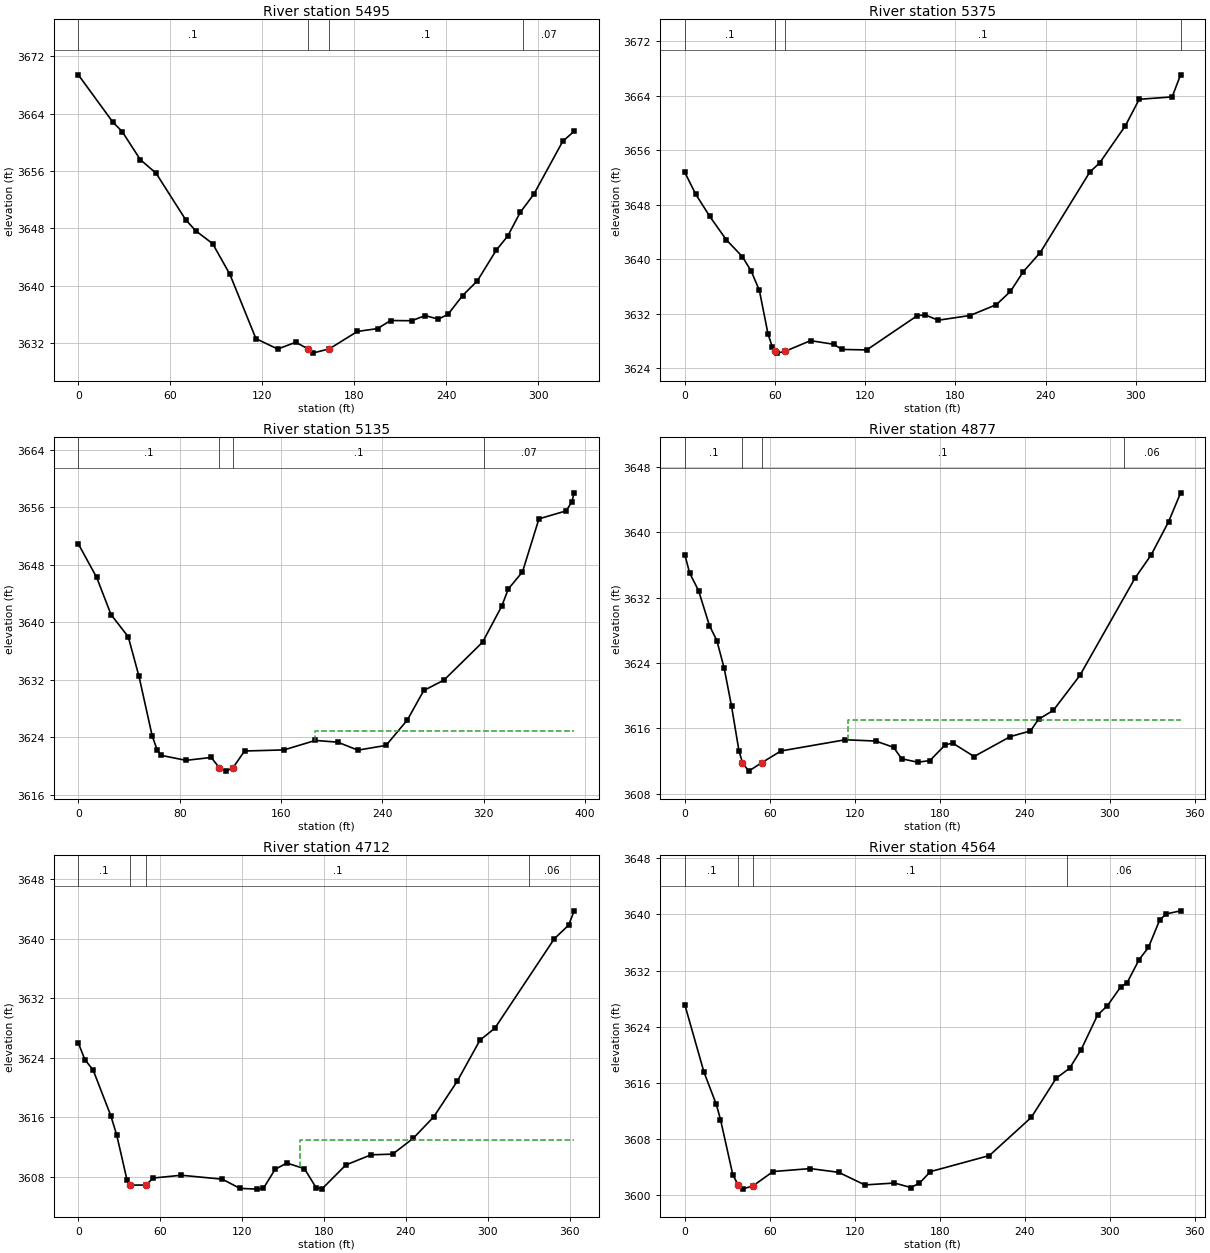
Type RM Length L Ch R = 1 ,5495    ,119.5,120.5,121.4
XS GIS Cut Line= 2
2365604.78348671626888.9286278042365823.92822577627126.558484985
#Sta/Elev= 30
       0 3669.42    22.4 3662.85    28.6  3661.5    40.4 3657.59    50.7 3655.69
    69.9 3649.23    76.5 3647.67    87.6 3645.86    98.8 3641.59   115.8 3632.61
     130 3631.16   141.8 3632.11   149.63631.197   152.7 3630.59   163.6 3631.18
     182 3633.62   195.1 3634.01   203.6 3635.14   217.4 3635.11   226.2 3635.83
   234.7 3635.33     241 3635.99   250.6 3638.63   260.2 3640.68   272.4 3644.92
     280 3646.93   288.2 3650.25     297 3652.76   315.9 3660.16   323.3 3661.54
#Mann= 4, -1 ,  0
       0     0.1       0   149.6   0.045       0   163.6     0.1       0
     290    0.07       0
Bank Sta=149.6,163.6
XS Rating Curve= 0 ,0
Exp/Cntr(USF)=0,0
Exp/Cntr=0.3,0.1

Type RM Length L Ch R = 1 ,5375    ,236.2,239.5,239.6
XS GIS Cut Line= 2
2365560.05864821627015.1779693882365800.23639876 627241.11136443
#Sta/Elev= 30
       0 3652.77     7.2 3649.59    16.6 3646.31    27.6 3642.88    38.3  3640.4
    44.1 3638.31    49.6 3635.45    55.3 3629.11    58.1 3627.21      603626.504
    61.3 3626.25    66.73626.516    83.6 3628.08      99 3627.55   104.5 3626.79
     121 3626.72   154.7 3631.76     160 3631.85   168.5 3631.08   189.7 3631.77
   207.2 3633.36   216.6 3635.31     225 3638.17   236.4 3641.01   269.3  3652.8
     276 3654.19     293 3659.61   302.2 3663.49   324.1 3663.84   329.7 3667.08
#Mann= 4, -1 ,  0
       0     0.1       0      60   0.045       0    66.7     0.1       0
  329.74    0.06       0
Bank Sta=60,66.7
XS Rating Curve= 0 ,0
Exp/Cntr(USF)=0,0
Exp/Cntr=0.3,0.1

Type RM Length L Ch R = 1 ,5135    ,258.3,258.1,254.9
XS GIS Cut Line= 2
 2365436.2635061 627129.785477172365677.27998355627438.178445569
#Sta/Elev= 30
       0 3650.88    14.5 3646.21    25.8 3641.05    39.4 3637.96    47.9 3632.44
    58.3 3624.17    62.2 3622.24    65.2 3621.47      85 3620.77   104.9 3621.17
   111.43619.717   116.3 3619.27     122 3619.71   131.2 3622.07   162.3 3622.22
   187.1 3623.54   204.7  3623.3   220.7 3622.19   242.9 3622.85   259.7 3626.38
   272.7 3630.49   288.6 3631.93   319.1 3637.21   334.3 3642.25   339.4 3644.61
   350.6 3646.99   363.6 3654.37   385.1 3655.48   389.6 3656.76   391.4 3657.99
#Mann= 4, -1 ,  0
       0     0.1       0   111.4   0.045       0     122     0.1       0
     320    0.07       0
#XS Ineff= 2 , 0
                           186.8         3624.85
Permanent Ineff=
       F       F
Bank Sta=111.4,122
XS Rating Curve= 0 ,0
Exp/Cntr(USF)=0,0
Exp/Cntr=0.3,0.1

Type RM Length L Ch R = 1 ,4877    ,165.9,164.5,162
XS GIS Cut Line= 2
 2365262.7859476627315.0124524872365532.07257887627538.585058634
#Sta/Elev= 30
       0 3637.28     3.4 3635.04     9.7 3632.88    17.4  3628.6    22.6 3626.77
    27.8 3623.38      33 3618.73    38.2 3613.29    40.73611.814    45.1 3610.78
    54.23611.799    67.9 3613.25   113.3 3614.62   134.9 3614.46   147.4 3613.69
   153.1 3612.29   164.4 3611.87     173 3612.07   183.8 3613.99     189 3614.22
   204.2 3612.57   229.8 3615.01     244  3615.7   249.7 3617.13   260.1 3618.21
   278.9  3622.5   317.8 3634.41   329.2 3637.25   341.5 3641.31     350 3644.85
#Mann= 4, -1 ,  0
       0     0.1       0    40.7   0.045       0    54.2     0.1       0
     310    0.06       0
#XS Ineff= 2 , 0
                          115.53            3617
Permanent Ineff=
       F       F
Bank Sta=40.7,54.2
XS Rating Curve= 0 ,0
Exp/Cntr(USF)=0,0
Exp/Cntr=0.3,0.1

Type RM Length L Ch R = 1 ,4712    ,146.9,148.7,148.8
XS GIS Cut Line= 2
2365154.01719793627453.0487034992365491.90919829627586.506323099
#Sta/Elev= 30
       0 3625.97     4.8 3623.74    10.9 3622.31    23.8 3616.18    28.1  3613.6
    35.7 3607.51    37.63606.841    49.6 3606.85    54.8 3607.79    75.4 3608.17
   105.5 3607.64   118.4  3606.4   131.2  3606.3   135.6  3606.4   144.2 3608.97
   152.8 3609.81   165.7 3609.05   174.3 3606.47   178.6 3606.34     196 3609.55
   214.5 3610.92   230.3 3611.01   245.3 3613.13   260.4 3616.03   277.6 3620.82
   294.3 3626.36   305.2 3627.97   348.8 3640.02   359.3 3641.85   363.3 3643.77
#Mann= 4, -1 ,  0
       0     0.1       0    37.6   0.045       0    49.6     0.1       0
     330    0.06       0
#XS Ineff= 2 , 0
                          162.13         3612.88
Permanent Ineff=
       F       F
Bank Sta=37.6,49.6
XS Rating Curve= 0 ,0
Exp/Cntr(USF)=0,0
Exp/Cntr=0.3,0.1

Type RM Length L Ch R = 1 ,4564    ,128.6,129.9,131.3
XS GIS Cut Line= 2
2365078.29345355627552.6619925072365380.86587944627728.587906146
#Sta/Elev= 30
       0 3627.13    13.5 3617.52    22.2 3612.92    25.2 3610.74    33.9 3602.85
    37.93601.331    40.8 3600.81    48.4 3601.31    62.3 3603.32    88.6 3603.74
   108.6 3603.21   127.1 3601.41     148 3601.68   159.5 3601.04   165.6 3601.65
   173.4 3603.31     215  3605.6   244.6 3611.05   262.2 3616.64   271.6 3618.05
   279.8 3620.72   291.4 3625.66   298.3 3626.97   307.6 3629.64   312.2 3630.25
   320.7 3633.56   327.3  3635.3   335.3 3639.25   339.9 3640.08     350 3640.52
#Mann= 4, -1 ,  0
       0     0.1       0    37.9   0.045       0    48.4     0.1       0
     270    0.06       0
Bank Sta=37.9,48.4
XS Rating Curve= 0 ,0
Exp/Cntr(USF)=0,0
Exp/Cntr=0.3,0.1

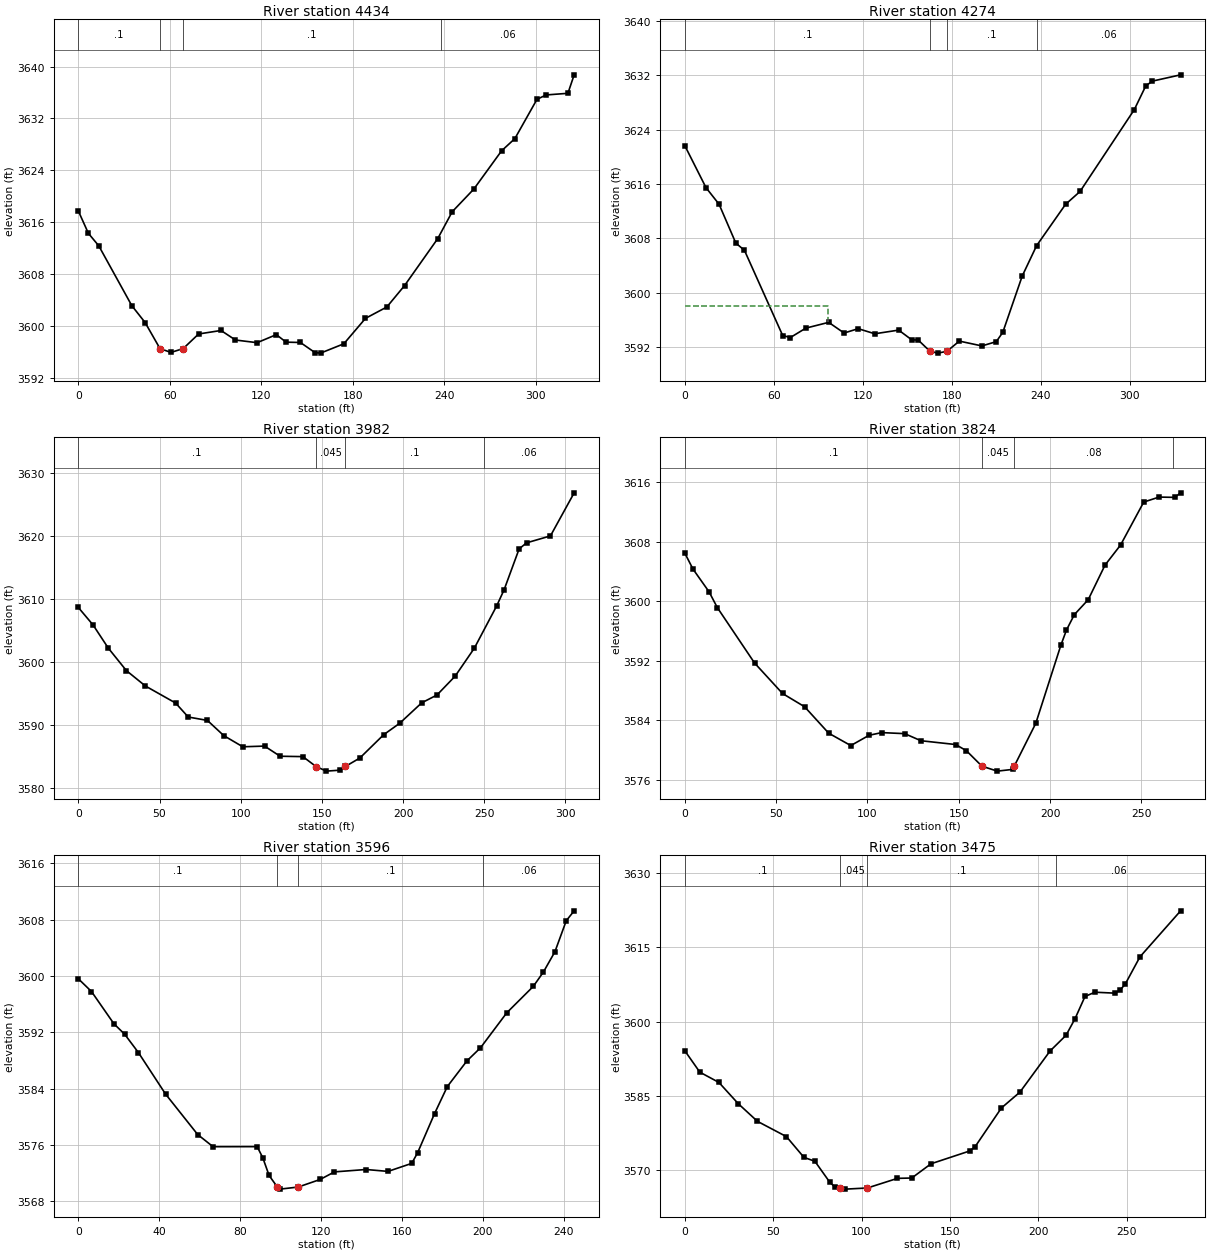
Type RM Length L Ch R = 1 ,4434    ,162.6,159.8,157.3
XS GIS Cut Line= 3
2365017.51420205627654.6026876522365087.19371762627707.848355206
2365287.68666335627835.375015769
#Sta/Elev= 30
       0 3617.75     6.6  3614.3    13.4 3612.38    35.1 3603.15    43.8 3600.56
    53.63596.528    60.8 3595.95    68.8 3596.54    78.9 3598.79    93.6 3599.33
   103.1 3597.86   117.3 3597.45   129.9 3598.69   136.3 3597.53   145.7 3597.48
   155.2 3595.93   158.9 3595.84   174.2 3597.28   188.4  3601.2   202.4 3602.95
     214 3606.24   235.8 3613.49   245.3 3617.63   259.5 3621.13   277.7 3627.02
   286.4  3628.9   300.9 3634.95   306.9 3635.63   321.2 3635.88   325.3 3638.73
#Mann= 4, -1 ,  0
       0     0.1       0    53.6   0.045       0    68.8     0.1       0
  237.69    0.06       0
Bank Sta=53.6,68.8
XS Rating Curve= 0 ,0
Exp/Cntr(USF)=0,0
Exp/Cntr=0.3,0.1

Type RM Length L Ch R = 1 ,4274    ,287.9,291.5,294.1
XS GIS Cut Line= 3
2364934.75826029627726.1336136722365021.79777091627832.193794622
2365201.54228692627912.979290127
#Sta/Elev= 30
       0 3621.64    14.3 3615.45    23.1 3613.01    34.4 3607.29    40.2 3606.23
      66 3593.68    71.2 3593.39    81.6 3594.77      97 3595.62   107.4 3594.05
   116.9 3594.69   128.1 3593.94   144.2 3594.48     153 3593.05   157.4 3593.01
   165.33591.363   170.5 3591.09   176.73591.353   185.1 3592.86   200.3 3592.15
     210 3592.78   214.4 3594.15   227.5 3602.44   237.2 3606.91   256.7 3612.99
   266.5 3614.89   303.1 3626.95   310.8 3630.43   315.2 3631.13   334.3 3632.06
#Mann= 4, -1 ,  0
       0     0.1       0   165.3   0.045       0   176.7     0.1       0
   237.2    0.06       0
#XS Ineff= 2 , 0
           96.75 3598.03
Permanent Ineff=
       F       F
Bank Sta=165.3,176.7
XS Rating Curve= 0 ,0
Exp/Cntr(USF)=0,0
Exp/Cntr=0.3,0.1

Type RM Length L Ch R = 1 ,3982    ,155.7,158.8,158.9
XS GIS Cut Line= 2
2364763.95499268627849.0519571492364914.61135376628114.717938638
#Sta/Elev= 30
       0  3608.6     9.1 3605.82    18.5 3602.14    29.6 3598.59    41.3 3596.15
    59.9 3593.45    67.7 3591.23    79.5 3590.69    89.6 3588.28   101.3 3586.51
   114.7 3586.62   124.3 3585.01   138.3 3584.95   146.4 3583.38   152.8 3582.65
   161.1  3582.8   164.53583.392   173.4 3584.73   188.1 3588.43   197.9 3590.23
   211.5 3593.48   220.9 3594.72   232.1 3597.71   243.9 3602.14   257.7 3608.86
   262.3 3611.44   271.5 3617.89   276.1 3618.85   290.8 3619.95   305.4 3626.78
#Mann= 4, -1 ,  0
       0     0.1       0   146.4   0.045       0   164.5     0.1       0
     250    0.06       0
Bank Sta=146.4,164.5
XS Rating Curve= 0 ,0
Exp/Cntr(USF)=0,0
Exp/Cntr=0.3,0.1

Type RM Length L Ch R = 1 ,3824    ,226.3,227.9,224.2
XS GIS Cut Line= 3
 2364673.3152473627913.140640054 2364693.6436826627956.006801934
2364765.06529123628168.330823243
#Sta/Elev= 30
       0 3606.46     4.5 3604.31    13.3 3601.26    17.8 3599.15    38.2 3591.71
    53.5 3587.62    65.6 3585.84    78.8 3582.29    90.9 3580.63   100.9 3582.01
   107.8 3582.37   120.4 3582.23   129.3 3581.28   148.3 3580.77   154.2 3579.94
   162.73577.865   171.1  3577.2   179.5 3577.43   180.43577.864   192.2 3583.62
   205.9 3594.08     209 3596.14   213.3  3598.2   220.9 3600.21   230.1 3604.85
   238.6 3607.54   251.3 3613.31   259.7 3613.98   268.3 3613.94   271.5 3614.55
#Mann= 4, -1 ,  0
       0     0.1       0   162.7   0.045       0   180.4    0.08       0
  267.44     0.1       0
Bank Sta=162.7,180.4
XS Rating Curve= 0 ,0
Exp/Cntr(USF)=0,0
Exp/Cntr=0.3,0.1

Type RM Length L Ch R = 1 ,3596    ,123.2,121,120.9
XS GIS Cut Line= 2
2364463.99247202628020.4237348992364630.84718319628200.016753012
#Sta/Elev= 30
       0 3599.61     6.5  3597.8    17.6 3593.21    22.9 3591.73    29.7 3589.12
    43.1 3583.23      59 3577.47    66.6 3575.74    88.4 3575.75    91.2 3574.16
    94.3 3571.65    98.43569.999    99.7 3569.71   108.73570.008   119.5 3571.08
   126.6 3572.16   142.2  3572.5   153.1 3572.23   164.8 3573.37   167.7 3574.87
   176.1 3580.45   182.4 3584.29   192.1 3587.94   198.8  3589.8   211.8 3594.78
   224.9 3598.53   229.9 3600.57   235.6 3603.46   241.2 3607.87   245.1 3609.27
#Mann= 4, -1 ,  0
       0     0.1       0    98.4   0.045       0   108.7     0.1       0
     200    0.06       0
Bank Sta=98.4,108.7
XS Rating Curve= 0 ,0
Exp/Cntr(USF)=0,0
Exp/Cntr=0.3,0.1

Type RM Length L Ch R = 1 ,3475    ,155.8,157.8,158.4
XS GIS Cut Line= 2
2364365.99858425628095.3903018592364571.69226803628286.063652271
#Sta/Elev= 30
       0 3594.12     8.5  3589.8    19.3 3587.73    30.2 3583.46    41.1 3579.89
    57.5 3576.81    67.4 3572.63    73.6 3571.84    81.9 3567.68    84.8 3566.68
    87.7 3566.44    90.9 3566.23   103.33566.461   120.3  3568.4   128.4 3568.47
   139.3 3571.34   161.1 3573.91   164.1 3574.71   179.1 3582.58   189.6 3585.78
   206.6 3594.05   215.7 3597.24   220.8  3600.6   226.4 3605.05     232 3605.91
   243.4 3605.72   246.2 3606.33   249.1  3607.5   257.5 3613.04   280.5 3622.31
#Mann= 4, -1 ,  0
       0     0.1       0    87.7   0.045       0   103.3     0.1       0
     210    0.06       0
Bank Sta=87.7,103.3
XS Rating Curve= 0 ,0
Exp/Cntr(USF)=0,0
Exp/Cntr=0.3,0.1

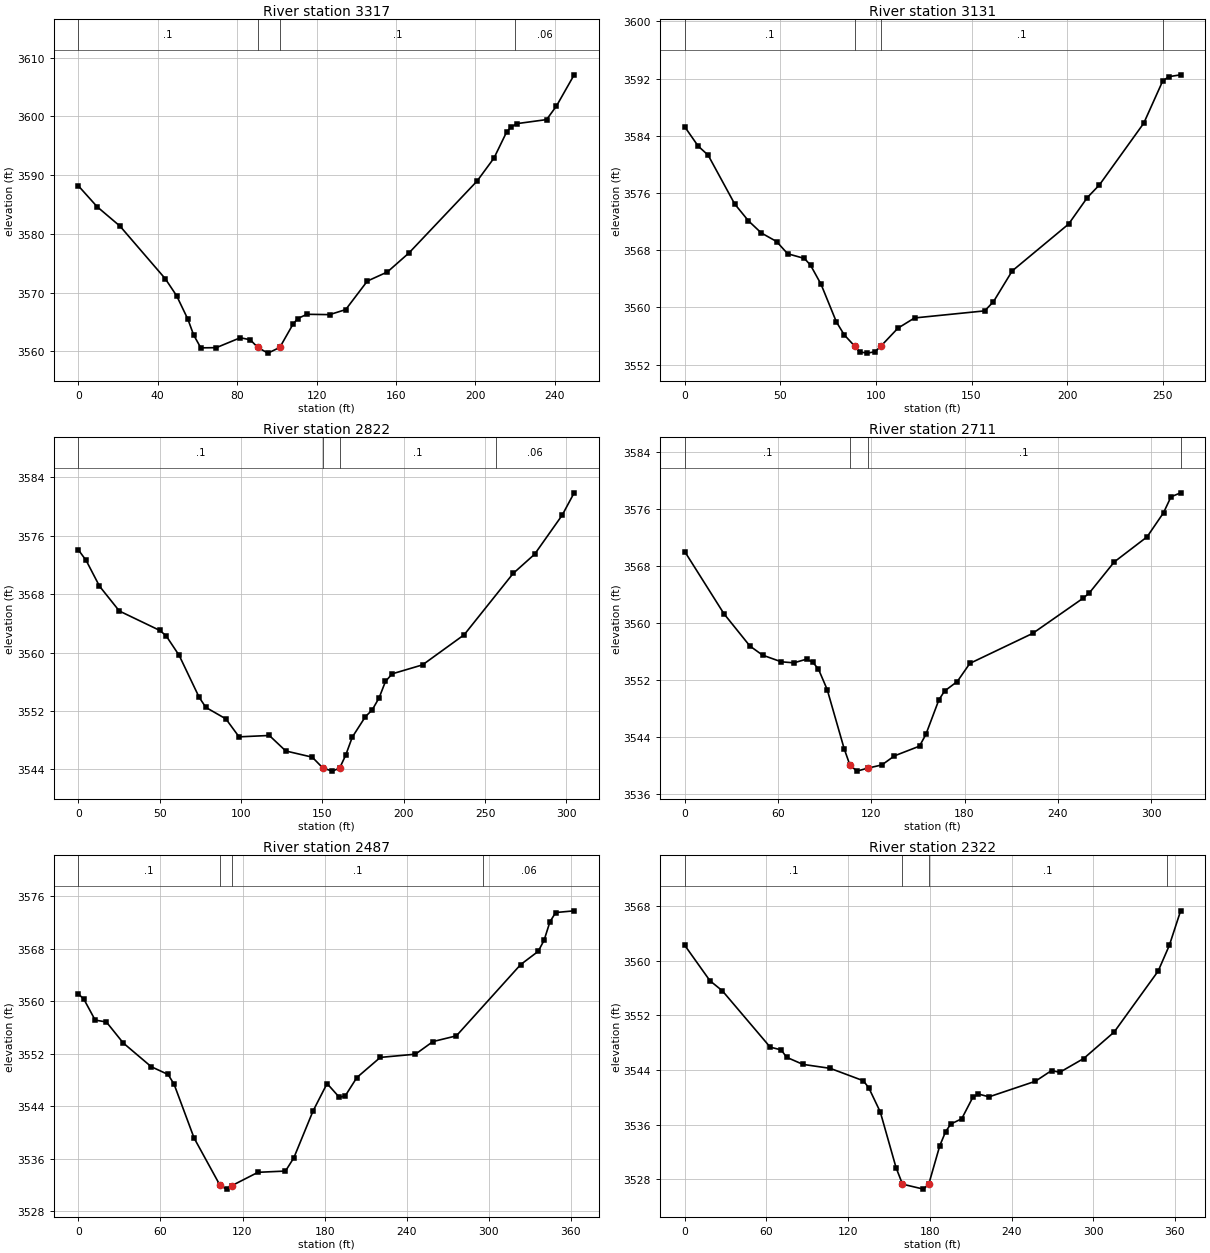
Type RM Length L Ch R = 1 ,3317    ,180.7,185.4,187.7
XS GIS Cut Line= 2
2364258.94134535628185.0412237342364409.62880563628384.245709462
#Sta/Elev= 30
       0 3588.19     9.5 3584.61      21 3581.31    43.8 3572.35    49.5 3569.46
    55.2 3565.44    58.1 3562.76    61.7 3560.57    69.5  3560.6    81.6 3562.29
    86.6 3561.95    90.43560.642    95.5 3559.67   101.5 3560.64   108.1 3564.57
   110.5 3565.56   115.2 3566.29   126.6 3566.23   134.7 3567.09   145.6 3571.95
   155.7  3573.5   166.6 3576.75   200.9    3589   209.4 3592.91   215.8 3597.37
     218 3598.18   220.9 3598.78   235.9 3599.47   240.9 3601.79   249.8  3607.1
#Mann= 4, -1 ,  0
       0     0.1       0    90.4   0.045       0   101.5     0.1       0
     220    0.06       0
Bank Sta=90.4,101.5
XS Rating Curve= 0 ,0
Exp/Cntr(USF)=0,0
Exp/Cntr=0.3,0.1

Type RM Length L Ch R = 1 ,3131    ,308.6,309.4,310.1
XS GIS Cut Line= 4
2364121.17983996628246.613858768 2364153.4916498628302.349449189
2364160.71648213628367.7843910492364235.78295013628472.864689453
#Sta/Elev= 30
       0 3585.24       7 3582.55    12.2 3581.29    26.1 3574.46    33.3  3572.1
      40 3570.41      48 3569.21    53.8  3567.5    62.6 3566.84    65.8 3565.89
    71.3 3563.22    79.3 3557.97    83.4 3556.16    88.8  3554.6    91.4 3553.78
    95.4  3553.6    99.5 3553.79   102.63554.578   111.5 3557.09   120.2 3558.52
   156.9 3559.51   161.5  3560.8   171.3  3565.1   200.8 3571.65   210.6 3575.36
   216.9 3577.12   240.1 3585.75     250 3591.64   253.2 3592.26   259.4 3592.52
#Mann= 4, -1 ,  0
       0     0.1       0    88.8   0.045       0   102.6     0.1       0
  250.26    0.06       0
Bank Sta=88.8,102.6
XS Rating Curve= 0 ,0
Exp/Cntr(USF)=0,0
Exp/Cntr=0.3,0.1

Type RM Length L Ch R = 1 ,2822    ,112.1,111.2,108
XS GIS Cut Line= 3
2363946.73916417628324.5005033422363903.82713711628526.495360755
2363956.09887814628609.717168335
#Sta/Elev= 30
       0 3574.05     4.8  3572.6      13 3569.08    25.2 3565.68      50 3563.03
    53.9 3562.31      62  3559.6    74.3 3553.86    78.4 3552.49    90.7 3550.92
    98.8 3548.46   117.4 3548.65   127.5 3546.53   143.8 3545.68   150.3  3544.2
   156.1 3543.77   160.63544.171   164.3 3545.92   168.4 3548.42   176.5 3551.23
   180.6 3552.13   184.9  3553.8   188.8 3556.04   192.9 3557.08   211.6 3558.31
   237.2 3562.43   267.3 3570.82   280.5 3573.45   297.4 3578.78   304.8 3581.85
#Mann= 4, -1 ,  0
       0     0.1       0   150.3   0.045       0   160.6     0.1       0
   256.5    0.06       0
Bank Sta=150.3,160.6
XS Rating Curve= 0 ,0
Exp/Cntr(USF)=0,0
Exp/Cntr=0.3,0.1

Type RM Length L Ch R = 1 ,2711    ,225,223.5,220.8
XS GIS Cut Line= 2
2363800.00671441628347.7548882632363846.46032487 628663.33235223
#Sta/Elev= 30
       0 3569.99    25.2 3561.29    41.9 3556.77      50  3555.5    62.1 3554.56
    70.2 3554.42    78.3 3554.93    82.3 3554.52      86 3553.53    91.6 3550.68
   102.5 3542.41   106.23540.115   110.7 3539.25   117.6 3539.66   126.8 3540.12
   134.9 3541.39     151 3542.75   155.1 3544.39   163.5 3549.25   167.2 3550.48
   175.3  3551.8   183.4 3554.34   223.8 3558.54   256.2 3563.46   260.2 3564.19
   276.3 3568.55   297.4 3572.06     308 3575.44   312.8 3577.67     319 3578.23
#Mann= 4, -1 ,  0
       0     0.1       0   106.2   0.045       0   117.6     0.1       0
  318.98    0.06       0
Bank Sta=106.2,117.6
XS Rating Curve= 0 ,0
Exp/Cntr(USF)=0,0
Exp/Cntr=0.3,0.1

Type RM Length L Ch R = 1 ,2487    ,162,165.7,172.1
XS GIS Cut Line= 4
2363562.74832779628397.2032252122363577.72779129628463.322923589
2363644.77789117628560.6113038112363706.82614245628725.761378631
#Sta/Elev= 30
       0 3561.11     4.1 3560.27    12.3 3557.11    20.5 3556.82    32.8 3553.63
    53.3 3550.01    65.6 3548.83      70 3547.34    84.6 3539.16   103.6 3531.94
   108.3 3531.38   112.4 3531.93   131.3 3533.94   151.4 3534.13   157.5 3536.14
   171.5 3543.25   181.8 3547.45   190.8 3545.35   195.1 3545.58   203.6 3548.37
   220.7 3551.43   246.4 3551.92   259.2 3553.84   276.3 3554.71   323.3 3565.56
   336.1 3567.57   340.4 3569.25   344.7 3572.07   348.9 3573.48   362.4 3573.74
#Mann= 4, -1 ,  0
       0     0.1       0   103.6   0.045       0   112.4     0.1       0
  295.95    0.06       0
Bank Sta=103.6,112.4
XS Rating Curve= 0 ,0
Exp/Cntr(USF)=0,0
Exp/Cntr=0.3,0.1

Type RM Length L Ch R = 1 ,2322    ,275.1,273.5,268.5
XS GIS Cut Line= 3
2363453.43566785628418.7720445062363477.69202752628661.927259669
2363532.39620457628768.579232529
#Sta/Elev= 30
       0 3562.22    18.5 3557.04    27.6 3555.57    62.7 3547.33    70.8 3546.92
    74.8 3545.84    86.8  3544.8   106.8 3544.22   131.1 3542.41   135.1 3541.39
   143.6 3537.83   155.2 3529.67   159.93527.267   175.3 3526.54   179.23527.271
   187.3  3532.9   191.6 3534.96   195.4 3536.07   203.4 3536.84   211.5 3539.96
   215.5 3540.47   223.5 3540.05   257.5 3542.33   269.4  3543.9   275.4 3543.64
     293 3545.66   315.4 3549.54   347.7 3558.46   355.9 3562.22   364.2 3567.28
#Mann= 4, -1 ,  0
       0     0.1       0   159.9   0.045       0   179.2     0.1       0
  354.36    0.06       0
Bank Sta=159.9,179.2
XS Rating Curve= 0 ,0
Exp/Cntr(USF)=0,0
Exp/Cntr=0.3,0.1

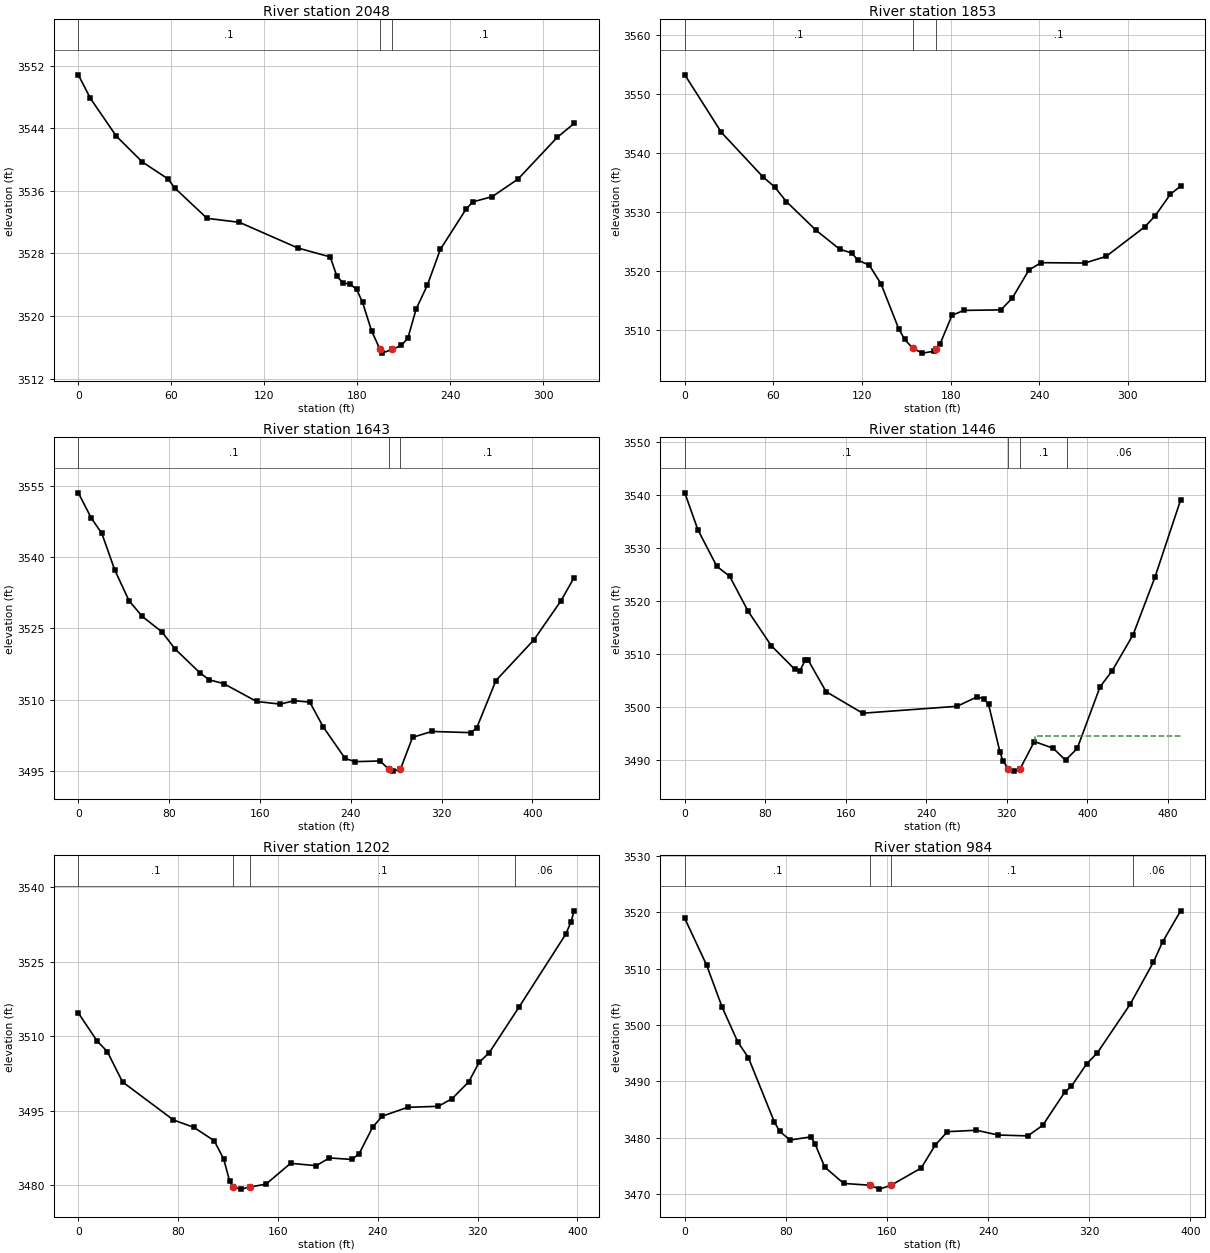
Type RM Length L Ch R = 1 ,2048    ,193.6,195,195.2
XS GIS Cut Line= 2
2363179.09677079628521.723693622 2363273.0158693628827.771759551
#Sta/Elev= 30
       0 3550.81     7.8  3547.8    24.5 3542.98    41.3 3539.68      58  3537.5
    62.2 3536.36    83.1 3532.48     104 3531.97   141.7 3528.69   162.6 3527.55
   166.9  3525.1     171 3524.19   175.2 3524.12   179.7 3523.39   183.5 3521.74
   189.3 3518.11   194.83515.728   196.1 3515.26   202.8 3515.75   208.6 3516.25
   212.8 3517.21   218.1  3520.9   225.4 3523.98   233.7 3528.51   250.5 3533.71
   254.7 3534.58   267.2 3535.25   283.9  3537.5   309.1 3542.81   320.1  3544.6
#Mann= 3, -1 ,  0
       0     0.1       0   194.8   0.045       0   202.8     0.1       0
Bank Sta=194.8,202.8
XS Rating Curve= 0 ,0
Exp/Cntr(USF)=0,0
Exp/Cntr=0.3,0.1

Type RM Length L Ch R = 1 ,1853    ,214.4,210.2,203.6
XS GIS Cut Line= 3
2363041.09502117628548.351063606 2363045.8105018628755.402987152
2363115.10057846628863.728868021
#Sta/Elev= 30
       0  3553.2    24.8 3543.43    52.8 3535.92    60.8 3534.19    68.8  3531.7
    88.9 3526.83   104.9 3523.62   112.9 3522.99   117.3 3521.76   124.9 3520.92
   132.8 3517.77   144.9 3510.09   148.9 3508.32   154.43506.804   160.9    3506
   168.9 3506.33   170.3 3506.78   172.9  3507.6   180.9 3512.41   188.9 3513.25
     214 3513.33   221.7 3515.32     233  3520.1   241.2 3521.34   270.9 3521.28
   285.2  3522.4   311.5 3527.43   318.4 3529.27   328.8 3532.96   335.7 3534.32
#Mann= 3, -1 ,  0
       0     0.1       0   154.4   0.045       0   170.3     0.1       0
Bank Sta=154.4,170.3
XS Rating Curve= 0 ,0
Exp/Cntr(USF)=0,0
Exp/Cntr=0.3,0.1

Type RM Length L Ch R = 1 ,1643    ,197.8,197.2,196
XS GIS Cut Line= 3
2362769.45810906628574.3126329452362824.63601505628764.727064227
2362992.43883405628934.321973074
#Sta/Elev= 30
       0 3553.47    11.3 3548.22    20.7 3544.95    32.1 3537.26    44.6 3530.84
    56.2 3527.55    73.8 3524.24    85.2 3520.69   107.1 3515.68   115.4  3514.2
   127.9 3513.43   157.1 3509.66   177.9 3509.11   190.4 3509.83   203.9 3509.52
   215.8  3504.3     235  3497.7   243.9 3497.03   265.8 3497.17   273.43495.456
   277.2 3495.04   283.83495.458   294.4 3502.13   311.4 3503.37   345.5 3503.12
   350.8 3504.03   367.9 3514.06   401.5 3522.65   425.1 3530.77   436.8 3535.69
#Mann= 3, -1 ,  0
       0     0.1       0   273.4   0.045       0   283.8     0.1       0
Bank Sta=273.4,283.8
XS Rating Curve= 0 ,0
Exp/Cntr(USF)=0,0
Exp/Cntr=0.3,0.1

Type RM Length L Ch R = 1 ,1446    ,247.1,243.2,240.3
XS GIS Cut Line= 2
2362471.58928576628712.925085086 2362852.6763465629025.373830225
#Sta/Elev= 30
       0 3540.46      13 3533.47    31.9 3526.54    44.6 3524.68    62.8 3518.12
    85.9 3511.57   109.4 3507.07   114.3  3506.8   119.7  3508.8   122.8 3508.77
   140.4 3502.87   176.8 3498.79   270.6  3500.1   290.4 3501.87   296.9 3501.55
   301.9 3500.47   313.2 3491.49   316.1 3489.79   321.5  3488.3   327.5 3487.84
   333.33488.294   347.4 3493.44   366.3 3492.15   378.4  3489.9     390 3492.12
   412.7 3503.76   424.9 3506.86   445.6 3513.64   467.3 3524.52   492.8 3539.12
#Mann= 4, -1 ,  0
       0     0.1       0   321.5   0.045       0   333.3     0.1       0
     380    0.06       0
#XS Ineff= 2 , 0
                          348.48         3494.51
Permanent Ineff=
       F       F
Bank Sta=321.5,333.3
XS Rating Curve= 0 ,0
Exp/Cntr(USF)=0,0
Exp/Cntr=0.3,0.1

Type RM Length L Ch R = 1 ,1202    ,209.7,218.1,220.7
XS GIS Cut Line= 2
2362409.47608114629038.4089754762362798.78676471629117.953330639
#Sta/Elev= 30
       0 3514.67      15 3509.04    23.2  3506.9    35.4 3500.78    76.2 3493.11
    92.6 3491.62   108.9 3488.92   116.5 3485.24   121.2 3480.85     1243479.614
   130.1 3479.17   137.5 3479.59   150.4 3480.17   170.1 3484.37   190.6  3483.9
   201.3 3485.46   219.1 3485.15     225 3486.26   235.9 3491.67   243.6 3493.88
     264 3495.66   288.5 3495.86   299.6 3497.41   312.9 3500.79   321.2 3504.71
   329.4 3506.69   353.5 3515.97   390.6 3530.53   394.7 3532.91   397.4 3535.26
#Mann= 4, -1 ,  0
       0     0.1       0     124   0.045       0   137.5     0.1       0
     350    0.06       0
Bank Sta=124,137.5
XS Rating Curve= 0 ,0
Exp/Cntr(USF)=0,0
Exp/Cntr=0.3,0.1

Type RM Length L Ch R = 1 ,984     ,246.4,243.8,241.3
XS GIS Cut Line= 4
2362367.52556304629199.2064099642362462.47463282629223.964861627
2362589.08099789629360.6287416832362689.41028026629399.894502351
#Sta/Elev= 30
       0 3518.87    17.2 3510.63    29.6 3503.11      42 3496.95    50.3 3494.21
    70.9 3482.77    75.1 3481.14    83.3 3479.61    99.8 3480.17     103 3478.94
   110.7 3474.81   125.7 3471.92   146.4  3471.6     154 3470.91   163.2  3471.6
     187 3474.65   197.9 3478.65   207.7 3481.09   230.6 3481.34   247.8  3480.5
   271.3 3480.34   283.1 3482.21   300.6 3488.11   305.8 3489.13   317.8 3493.08
   326.4 3495.08   352.2 3503.64   370.6 3511.09   377.9  3514.7   392.2 3520.22
#Mann= 4, -1 ,  0
       0     0.1       0   146.4   0.045       0   163.2     0.1       0
  354.42    0.06       0
Bank Sta=146.4,163.2
XS Rating Curve= 0 ,0
Exp/Cntr(USF)=0,0
Exp/Cntr=0.3,0.1