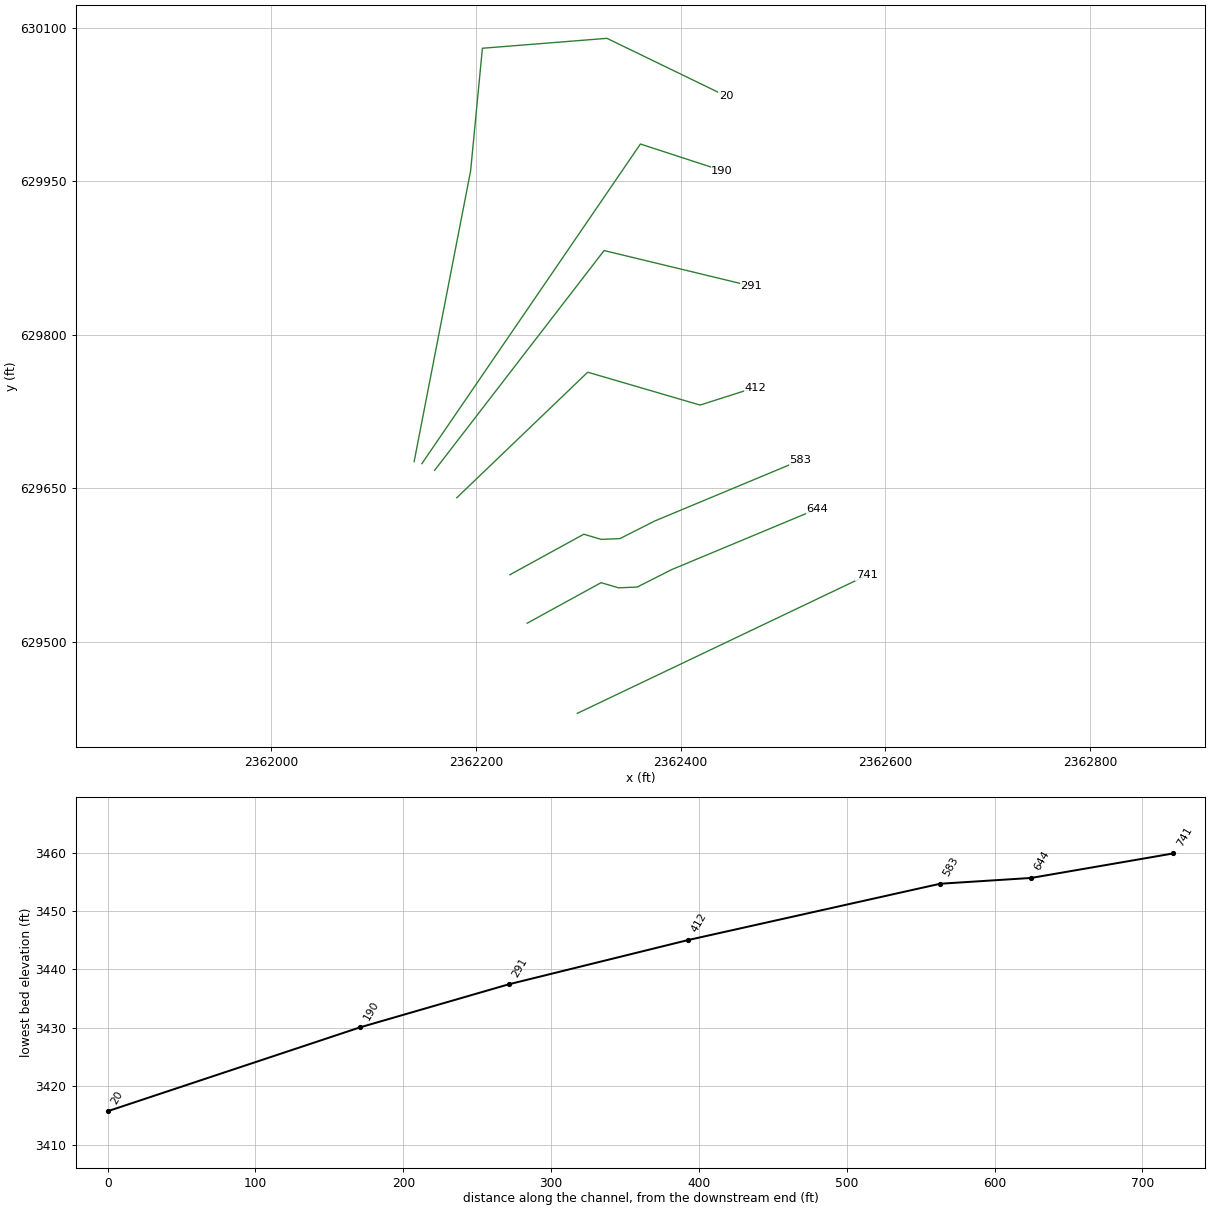
HEC-RAS study NARROWRDG.prj: NARROWRDG

--- NARROWRDG.g01 (geometry) --- (continued)

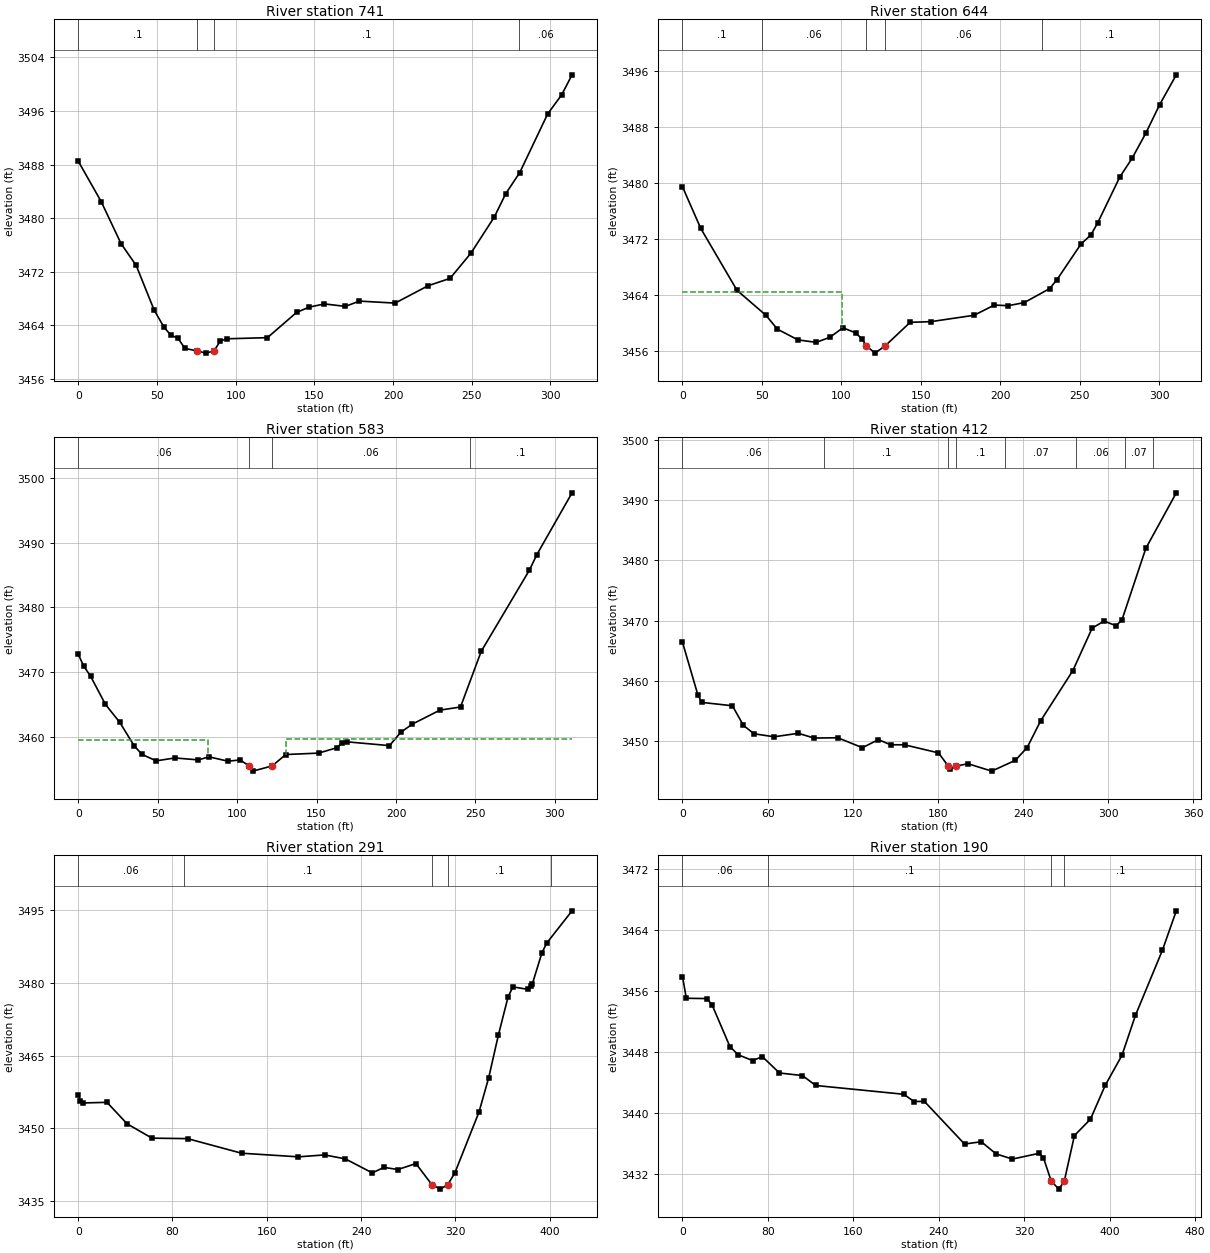
Type RM Length L Ch R = 1 ,741     ,99,96.3,95.4
XS GIS Cut Line= 2
2362299.00160583629430.060363553 2362582.1464036629565.052508542
#Sta/Elev= 30
       0 3488.52    14.6 3482.47    27.2  3476.2    36.8 3472.95    48.2 3466.29
    54.5 3463.71    58.9 3462.52    63.3 3462.08    67.8 3460.56    75.2 3460.19
    81.2 3459.85    86.33460.194    90.2 3461.64    94.4 3461.99   120.2 3462.16
   138.7 3465.93   146.7 3466.72   156.4  3467.2   169.7 3466.83   178.6 3467.62
   201.3 3467.32   222.3 3469.92   236.2 3471.01   249.5 3474.79   264.3 3480.17
   271.6 3483.67   280.5 3486.82   298.2 3495.57   307.1 3498.42   313.7 3501.41
#Mann= 4, -1 ,  0
       0     0.1       0    75.2   0.045       0    86.3     0.1       0
     280    0.06       0
Bank Sta=75.2,86.3
XS Rating Curve= 0 ,0
Exp/Cntr(USF)=0,0
Exp/Cntr=0.3,0.1

Type RM Length L Ch R = 1 ,644     ,61.4,61.5,59.7
XS GIS Cut Line= 6
2362250.06955082629518.2184861642362322.26748128629557.810899644
2362339.34656161 629552.764807732362357.59012468629553.541129563
2362391.36012441629570.6202098872362533.81518076629630.008830107
#Sta/Elev= 30
       0 3479.42    11.5 3473.47    34.3 3464.63    52.6 3461.04    59.7 3459.08
    72.7 3457.54    84.2 3457.19    92.7 3457.91     101 3459.27     109 3458.54
     113 3457.68   115.63456.717   121.2 3455.65   127.73456.717   143.3 3460.05
   156.4 3460.15   183.5 3461.06   196.3 3462.52     205 3462.43   215.1 3462.87
     231 3464.86   235.5 3466.08   250.8 3471.24     257 3472.53   261.3 3474.25
   275.2  3480.8     283  3483.5   291.7 3487.12   300.3 3491.15   310.8 3495.42
#Mann= 5, -1 ,  0
       0     0.1       0      50    0.06       0   115.6   0.045       0
   127.7    0.06       0  226.43     0.1       0
#XS Ineff= 2 , 0
          100.71 3464.32
Permanent Ineff=
       F       F
Bank Sta=115.6,127.7
XS Rating Curve= 0 ,0
Exp/Cntr(USF)=0,0
Exp/Cntr=0.3,0.1

Type RM Length L Ch R = 1 ,583     ,171.2,170.6,168.5
XS GIS Cut Line= 6
2362233.18455095629565.5741179732362305.38248142629605.166531453
2362322.46156174629600.1204395392362340.70512482629600.896761372
2362374.47512455629617.9758416962362516.93018089629677.364461916
#Sta/Elev= 30
       0 3472.76     3.4 3470.95     7.8 3469.34    17.1    3465    26.2 3462.19
    35.3 3458.54    40.2 3457.24    49.1 3456.25    60.8  3456.7    75.6  3456.4
    82.3 3456.87    94.2  3456.2   101.9 3456.39   107.43455.488   109.9 3454.66
   122.1 3455.47   130.6 3457.23   151.3 3457.45   162.6 3458.27   166.3 3459.04
   169.4 3459.19   195.9 3458.61     203 3460.67   210.3 3461.94   227.6  3464.1
   240.6 3464.59   253.6 3473.19     284 3485.79   288.6 3488.16   310.8 3497.75
#Mann= 4, -1 ,  0
       0    0.06       0   107.4   0.045       0   122.1    0.06       0
  246.43     0.1       0
#XS Ineff= 2 , 0
           81.95 3459.55  130.69         3459.58
Permanent Ineff=
       F       F
Bank Sta=107.4,122.1
XS Rating Curve= 0 ,0
Exp/Cntr(USF)=0,0
Exp/Cntr=0.3,0.1

Type RM Length L Ch R = 1 ,412     ,121.1,121.4,122.1
XS GIS Cut Line= 4
2362181.24640481 629640.823726222362309.19549838629763.535207394
2362419.04256167629731.4087201442362472.69600511629748.519581406
#Sta/Elev= 30
       0 3466.41    10.8 3457.71    13.6 3456.43    35.2 3455.87    42.9 3452.62
    50.4 3451.22    64.6 3450.72    81.6  3451.3    92.7 3450.51   109.4 3450.56
   126.8 3448.91   138.1 3450.25   146.6  3449.4   156.5 3449.39   180.4 3448.05
   187.33445.857   188.7 3445.44   192.9 3445.86   201.2 3446.25   217.9 3445.02
   234.6 3446.82   242.9 3448.94   252.5 3453.41   275.1 3461.71   288.7 3468.76
   297.1 3469.93   305.5 3469.16   309.7 3470.12   326.5 3481.99     348 3491.22
#Mann= 8, -1 ,  0
       0    0.06       0     100     0.1       0   187.3   0.045       0
   192.9     0.1       0  227.28    0.07       0  277.28    0.06       0
  311.73    0.07       0  331.73    0.06       0
Bank Sta=187.3,192.9
XS Rating Curve= 0 ,0
Exp/Cntr(USF)=0,0
Exp/Cntr=0.3,0.1

Type RM Length L Ch R = 1 ,291     ,94.4,100.5,109.1
XS GIS Cut Line= 3
2362159.55875051629667.6386515192362325.21913424629882.436283711
2362468.93724583629847.741710452
#Sta/Elev= 30
       0 3456.87     1.9  3455.6     4.4 3455.24    24.4 3455.37    41.5 3450.93
    62.6 3447.97    92.8 3447.87   138.6 3444.86   186.9 3444.11   209.1 3444.51
   226.8 3443.68   249.5  3440.8   259.6 3441.93   271.3 3441.49   286.6 3442.72
   300.13438.373   307.2 3437.44   313.63438.362   319.6 3440.77   340.1 3453.34
   348.4 3460.49   356.6 3469.29   364.8 3477.14   368.9 3479.22   381.3 3478.72
   384.1 3479.34   385.4 3479.82   393.6 3486.32   397.7  3488.3   419.1 3494.93
#Mann= 5, -1 ,  0
       0    0.06       0      90     0.1       0   300.1   0.045       0
   313.6     0.1       0  401.26    0.06       0
Bank Sta=300.1,313.6
XS Rating Curve= 0 ,0
Exp/Cntr(USF)=0,0
Exp/Cntr=0.3,0.1

Type RM Length L Ch R = 1 ,190     ,166.9,170.7,174.8
XS GIS Cut Line= 3
 2362147.1419572629674.1865617232362360.71624594629986.561144706
2362440.58474727629960.529929457
#Sta/Elev= 30
       0 3457.93     3.6 3455.09    23.1 3455.05    27.9 3454.16    44.4 3448.76
    52.1 3447.69    65.6 3446.93    74.8 3447.44    90.8  3445.3   112.3 3444.96
   124.8 3443.66   207.2 3442.51   216.8 3441.56   226.5 3441.58   264.1 3435.99
   279.8 3436.29   293.6  3434.7   308.9 3434.02   333.9 3434.77     338 3434.19
   345.3 3431.12   352.5 3430.08   357.53431.118     367  3437.1     382 3439.24
   395.8 3443.67   411.5 3447.61   424.1 3452.84   449.4 3461.39   462.4 3466.55
#Mann= 4, -1 ,  0
       0    0.06       0      80     0.1       0   345.3   0.045       0
   357.5     0.1       0
Bank Sta=345.3,357.5
XS Rating Curve= 0 ,0
Exp/Cntr(USF)=0,0
Exp/Cntr=0.3,0.1

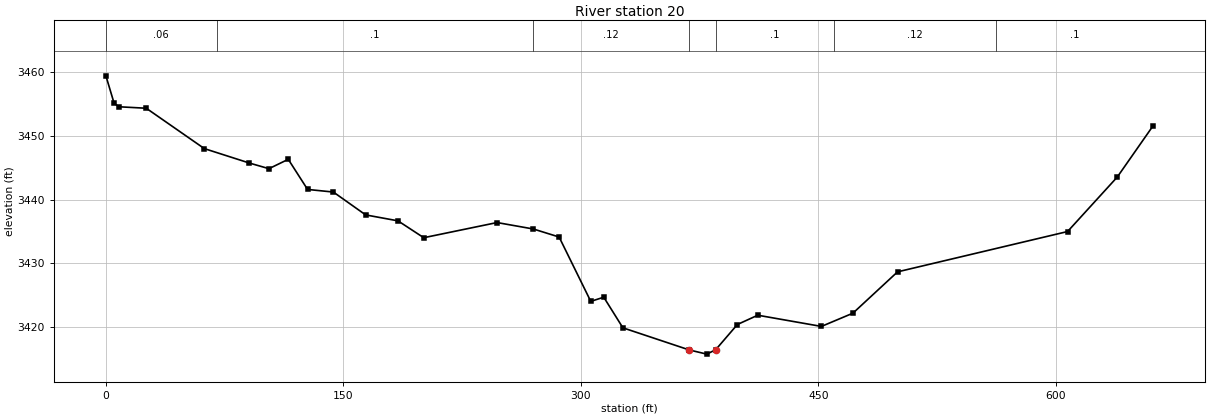
Type RM Length L Ch R = 1 ,20      ,,,
XS GIS Cut Line= 5
2362139.53687477629676.1048533512362194.75269649629960.262404015
2362206.27325717630080.1645002232362328.01473286630089.856314393
2362444.49050258630033.422936394
#Sta/Elev= 30
       0 3459.43     5.2 3455.11     8.3 3454.57    25.5 3454.34    62.2    3448
    90.7 3445.73     103 3444.85   115.2 3446.32   127.4 3441.59   143.7 3441.18
   164.1 3437.59   184.5 3436.66   200.8 3434.01   247.1 3436.39     270 3435.38
   286.3 3434.12   306.3 3424.01   314.5 3424.67   326.6 3419.86   368.6 3416.38
   379.6 3415.73   385.2 3416.42   398.9 3420.38   411.8 3421.84     452 3420.08
   471.9 3422.16   500.1 3428.65   607.5 3434.98   638.9 3443.54   661.5 3451.58
#Mann= 7, -1 ,  0
       0    0.06       0      70     0.1       0     270    0.12       0
   368.6   0.045       0   385.2     0.1       0  459.93    0.12       0
  562.05     0.1       0
Bank Sta=368.6,385.2
XS Rating Curve= 0 ,0
Exp/Cntr(USF)=0,0
Exp/Cntr=0.3,0.1
LCMann Table=0

Chan Stop Cuts=-1
Use User Specified Reach Order=0
Composite Channel Slope=5